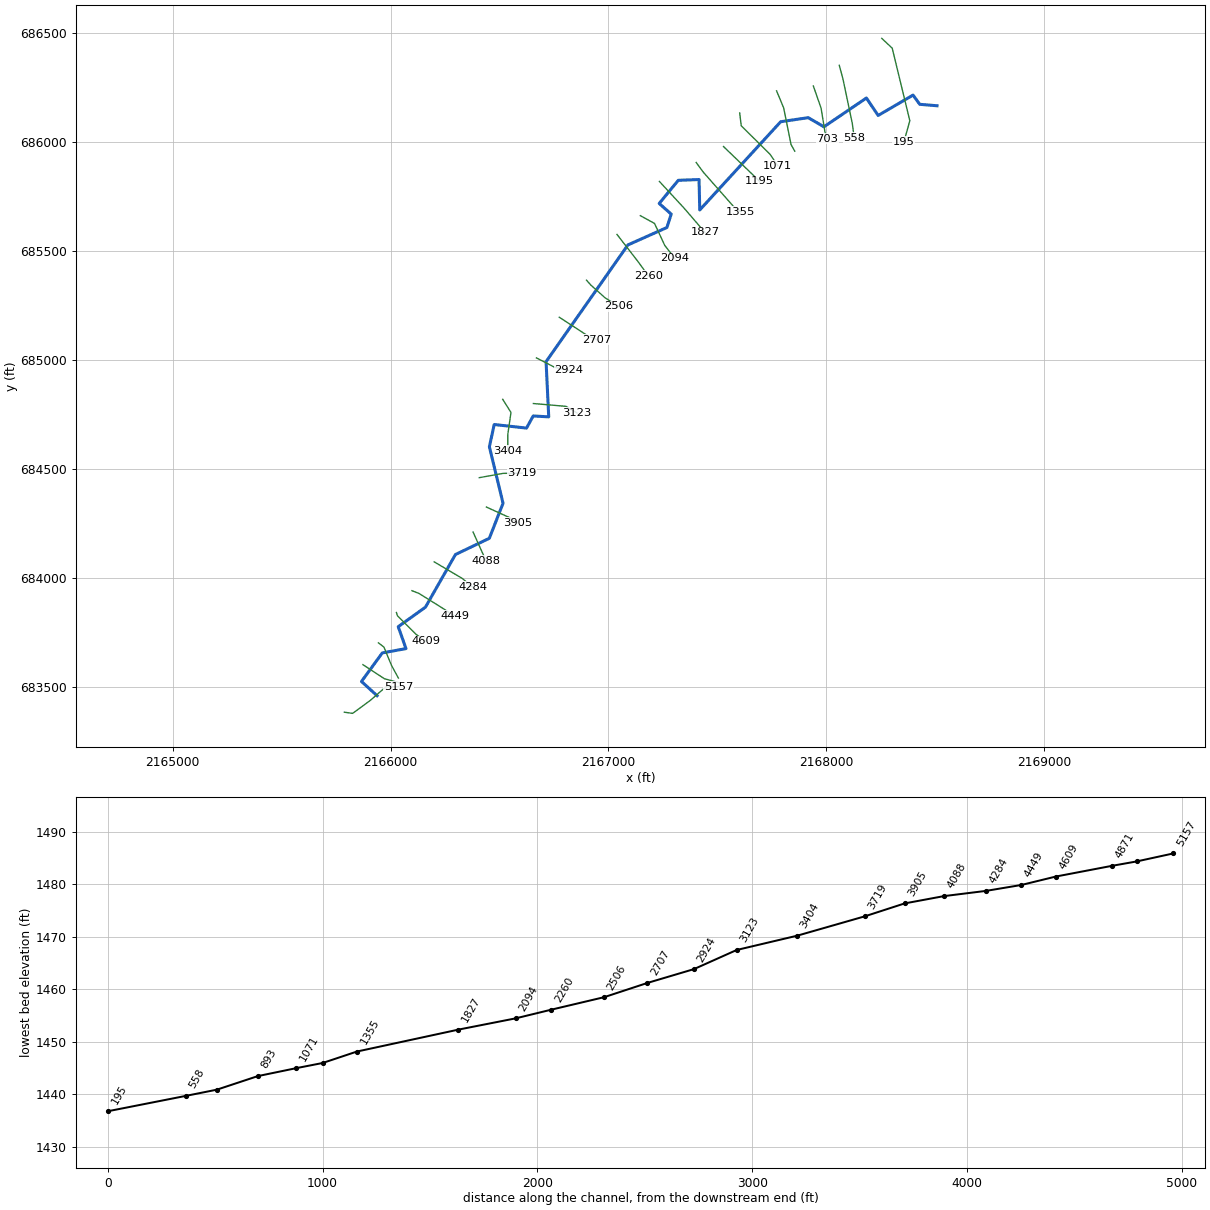
--- LIBRUSHRN.prj (project) ---

Proj Title=LIBRUSHRN
Current Plan=p01
Default Exp/Contr=0,0
English Units
Geom File=g01
Flow File=f01
Plan File=p01
BEGIN DESCRIPTION:
---------- MODELED AS PART OF WVEMD CTP PROGRAM, 2023----------
Stream Name: Little Brush Run
Flood Zone:  AFH
Upshur County, WV
HEC-RAS Version: RAS 6.3
Vertical Datum: NAVD88
Projection: NAD 1983 StatePlane West Virginia S FIPS 4702 (US Feet)
Terrain: 1-meter LIDAR (FEMA Region III 3DEP collected 2016-2018)
Land Use: 2019 NLCD
Hydrologic Method:
WV SIR2010-5033 regression equations
Additional Model Notes:
None
END DESCRIPTION:
DSS Export Rating Curves= 0
DSS Export Rating Curve Sorted= 0
DSS Export Volume Flow Curves= 0
DXF OffsetX= 0
DXF OffsetY= 0
DXF ScaleX= 0
DXF ScaleY= 0

--- LIBRUSHRN.p01 (plan) ---

Plan Title=Floodplain
Program Version=6.30
Short Identifier=Floodplain
Geom File=g01
Flow File=f01
Subcritical Flow
K Sum by GR= 0
Std Step Tol= 0.01
Critical Tol= 0.01
Num of Std Step Trials= 20
Max Error Tol= 0.3
Flow Tol Ratio= 0.001
Split Flow NTrial= 30
Split Flow Tol= 0.02
Split Flow Ratio= 0.02
Log Output Level= 0
Friction Slope Method= 1
Unsteady Friction Slope Method= 2
Unsteady Bridges Friction Slope Method= 1
Parabolic Critical Depth
Global Vel Dist= 0 , 0 , 0
Global Log Level= 0
CheckData=False
Encroach Param=-1 ,0,0, 0
Mapping Interval=1HOUR
Computation Time Step Use Courant=        0
Computation Time Step Use Time Series=    0
Computation Time Step Count To Double=0
Computation Time Step Max Doubling=0
Computation Time Step Max Halving=0
Computation Time Step Residence Courant=0
Run HTab= 0
Run UNet= 0
Run Sediment= 0
Run PostProcess= 0
Run WQNet= 0
Run RASMapper=-1
UNET Theta= 0
UNET Theta Warmup= 0
UNET ZTol= 0
UNET ZSATol= 0
UNET MxIter= 0
UNET Max Iter WO Improvement= 0
UNET MaxInSteps= 0
UNET DtIC= 0
UNET DtMin= 0
UNET MaxCRTS= 0
UNET WFStab= 0
UNET SFStab= 0
UNET WFX= 1
UNET SFX= 1
UNET Gravity=32.17405
UNET 1D Methodology=Finite Difference
UNET DSS MLevel= 1
UNET Pardiso=0
UNET DZMax Abort= 0
UNET Use Existing IB Tables= 0
UNET Froude Reduction=False
UNET Froude Limit= 0
UNET Froude Power= 0
UNET D1 Cores= 0
UNET WindReference=Eulerian
UNET WindDragFormulation=Hsu (1988)
UNET D2 Coriolis=0
UNET D2 Cores= 0
UNET D2 Theta= 1
UNET D2 Theta Warmup= 1
UNET D2 Z Tol= 0.01
UNET D2 Volume Tol= 0.01
UNET D2 Max Iterations= 20
UNET D2 Equation= 0
UNET D2 RampUpFraction=0.1
UNET D2 TimeSlices= 1
UNET D2 Turbulence Formulation=Non-Conservative (original)
UNET D2 Eddy Viscosity=0.3
UNET D2 Transverse Eddy Viscosity=0.1
UNET D2 Smagorinsky Mixing=0
UNET D2 BCVolumeCheck=0
UNET D2 Cores=0
UNET D2 SolverType=PARDISO (Direct)
UNET D2 Minimum Iterations= 3
UNET D2 Maximum Iterations= 30
UNET D2 Restart Number= 10
UNET D2 Relaxation Coeff=1.3
UNET D2 SOR Precondition Iterations= 10
UNET D2 ILUT Maximum Fill= 8
UNET D2 ILUT Tolerance=1E-08
UNET D2 Convergence Tolerance=0.00001
UNET D1D2 MaxIter= 0
UNET D1D2 ZTol=0.01
UNET D1D2 QTol=0.1
UNET D1D2 MinQTol=1
Write IC File= 0
Write IC File at Fixed DateTime=0
Write IC File at Sim End=0
Echo Input=False
Echo Parameters=False
Echo Output=False
Write Detailed= 0
HDF Write Warmup=0
HDF Write Time Slices=0
HDF Flush=0
HDF Compression= 1
HDF Chunk Size= 1
HDF Spatial Parts= 1
HDF Use Max Rows=0
HDF Fixed Rows= 1
Calibration Method= 0
Calibration Iterations= 20
Calibration Max Change=0.05
Calibration Tolerance=0.2
Calibration Maximum=1.5
Calibration Minimum=0.5
Calibration Optimization Method= 1
WQ AD Non Conservative
WQ ULTIMATE=-1
WQ Max Comp Step=1HOUR
WQ Output Interval=15MIN
WQ Output Selected Increments= 0
WQ Output face flow=0
WQ Output face velocity=0
WQ Output face area=0
WQ Output face dispersion=0
WQ Output cell volume=0
WQ Output cell surface area=0
WQ Output cell continuity=0
WQ Output cumulative cell continuity=0
WQ Output face conc=0
WQ Output face dconc_dx=0
WQ Output face courant=0
WQ Output face peclet=0
WQ Output face adv mass=0
WQ Output face disp mass=0
WQ Output cell mass=0
WQ Output cell source sink temp=0
WQ Output nsm pathways=0
WQ Output nsm derived pathways=0
WQ Create Restart=0
WQ Fixed Restart=0
WQ System Summary=0
WQ Write To DSS=0
Sorting and Armoring Iterations= 10
XS Update Threshold= 0.02
Bed Roughness Predictor= 0
Hydraulics Update Threshold= 0.02
Energy Slope Method= 1
Volume Change Method= 1
Sediment Retention Method= 0
Sediment TS Multiplier= 1
Warm Up Method= 0
XS Weighting Method= 0
Number of US Weighted Cross Sections= 1
Number of DS Weighted Cross Sections= 1
Upstream XS Weight=0
Main XS Weight=1
Downstream XS Weight=0
Number of DS XS's Weighted with US Boundary= 1
Upstream Boundary Weight= 1
Weight of XSs Associated with US Boundary= 0
Number of US XS's Weighted with DS Boundary= 1
Downstream Boundary Weight= 0.5
Weight of XSs Associated with DS Boundary= 0.5
Percentile Method= 0
Sediment Output Level= 3
Mass or Volume Output= 0
Output Increment Type= 1
Profile and TS Output Increment= 1
Transport Output Increment 1
XS Output Flag= 0
XS Output Increment= 10
Read HDF5 Sediment Hotstart= 0
Sediment Hotstart Type= 0
Write Gradation File= 0
Read Gradation Hotstart= 0
Write HDF5 File= 1
Write Binary Output= 1
Write DSS Sediment File= 0
DSS Sediment Output Type= 1
SV Curve= 0
Specific Gage Flag= 0
Subcell Erosion Methods= 0
Subcell Deposition Methods= 0
Advection Scheme= 1
Matrix Solver= 0
Implicit Weighting Factor= 1
Maximum Outer Loop Convergence Iterations= 5
Convergence Maximum Absolute= 0.001
Convergence RMSE= 0.0001
Grain Fractions Max Abs Error= 0.001
Max Subgrid Regions= 1
Max Subgrid Length Scale= 3.402823E+38
Initial Layer Thickness= 3.402823E+38
Min Layer Thickness= 3.402823E+38
Max Layer Thickness= 3.402823E+38
Number of Layers= 5

--- LIBRUSHRN.f01 (steady flow) ---

Flow Title=Flows
Program Version=6.30
Number of Profiles= 1
Profile Names=01pct
River Rch & RM=LIBRUSHRN,Main,5157
     378
Boundary for River Rch & Prof#=LIBRUSHRN,Main            , 1
Up Type= 0
Dn Type= 3
Dn Slope=0.008
DSS Import GetInterval= 0
DSS Import GetPeak= 0
DSS Import FillOption= 0

--- LIBRUSHRN.g01 (geometry) ---

Geom Title=Geometry
Program Version=6.30

River Reach=LIBRUSHRN       ,Main
Reach XY= 30
2165938.33789791683458.9710166082165866.79383068683524.393670293
2165962.36410608683655.4163804452166070.99233835683675.117660445
     2166035.488      683775.676     2166160.256      683865.246
     2166298.015      684106.911     2166453.402      684181.256
     2166516.387      684342.109     2166453.746      684601.488
     2166475.866      684703.477     2166624.156      684687.108
     2166654.747      684742.681     2166726.088      684738.675
     2166713.869      684991.873     2167089.459      685527.629
     2167268.397      685607.554     2167288.085      685669.137
     2167232.941      685717.842     2167320.679      685824.152
     2167415.886        685827.7     2167419.148      685688.138
     2167790.503      686092.974      2167916.93      686111.632
     2167989.043      686069.766     2168183.892      686201.802
     2168237.834      686121.762        2168398.      686215.281
      2168428.62      686172.928     2168507.887      686166.289

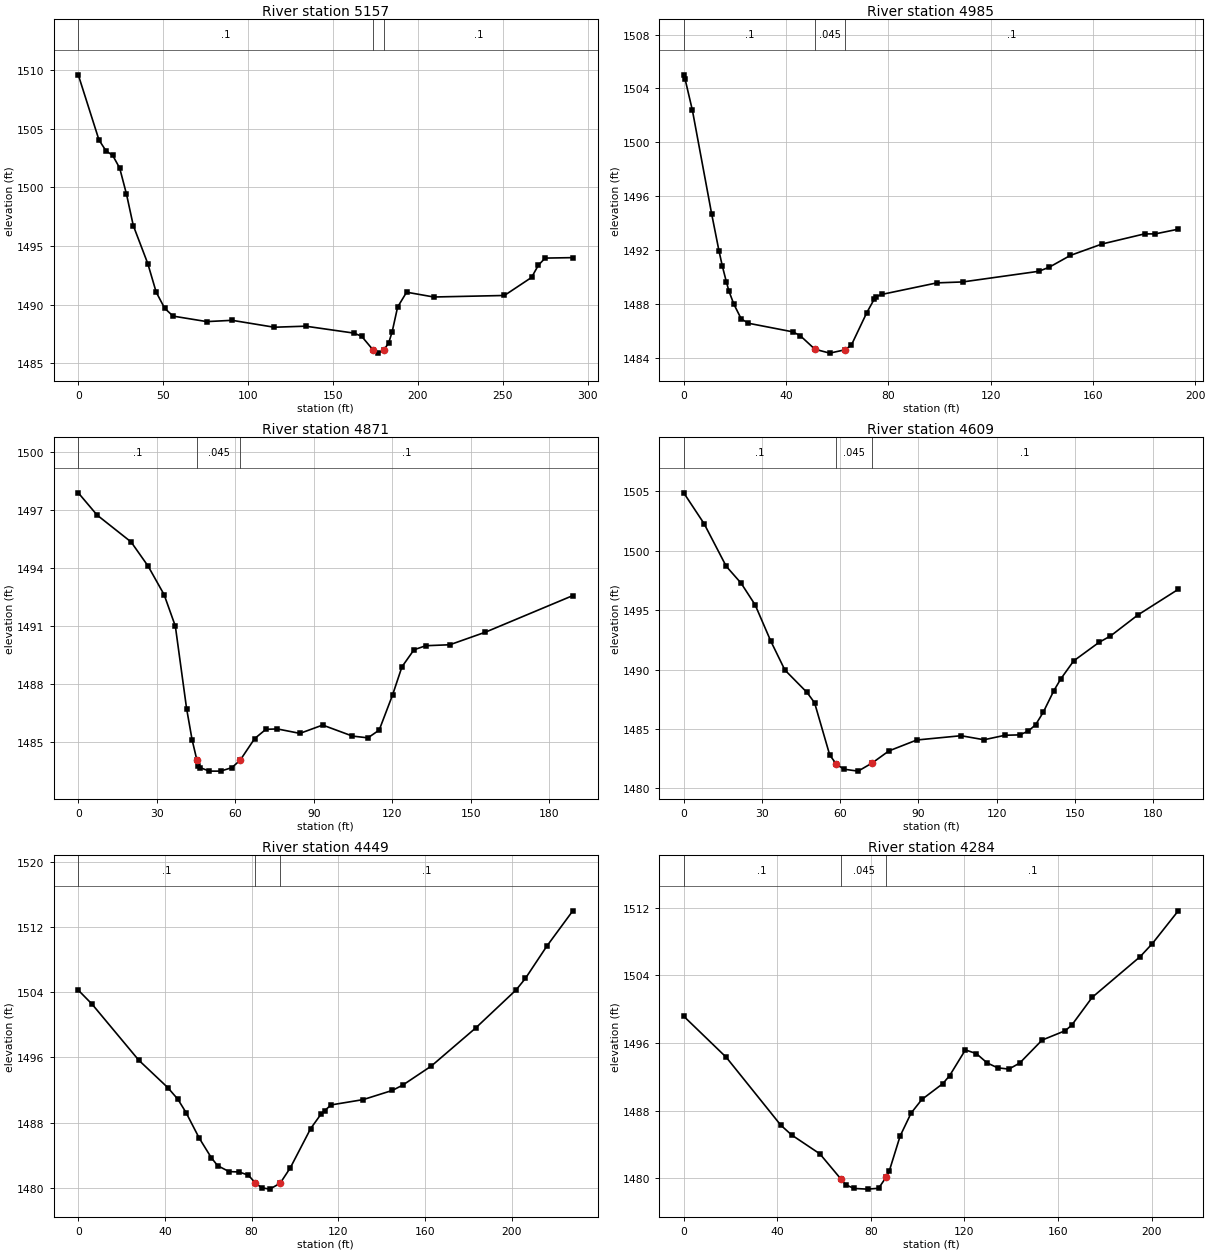
Type RM Length L Ch R = 1 ,5157    ,171.4,171.4,171.4
XS GIS Cut Line= 5
2165788.05064791683383.2369257652165826.23697981683377.893857892
2165906.89953007683437.1004302632165977.21199861683498.531323831
2166036.42249843683501.121783198
#Sta/Elev= 30
       0 1509.61    12.2 1504.05    16.3 1503.13    20.3 1502.73    24.4 1501.65
    28.4 1499.43    32.4 1496.75      41 1493.48    45.9 1491.06    50.9 1489.69
    55.8 1489.02    75.7 1488.55    90.6 1488.66   115.4 1488.07   133.9 1488.16
   162.3 1487.57   166.9  1487.3   173.6 1486.14   176.4 1485.86     1801486.146
   182.8 1486.71   184.9 1487.69   188.1 1489.79   193.4 1491.06   209.4 1490.65
     251 1490.78     267 1492.32     271 1493.36     275 1493.97   291.3 1494.01
#Mann= 3 ,-1,0
       0      .1       0   173.6    .045       0     180      .1       0
Bank Sta=173.6,180
XS Rating Curve= 0 ,0
Exp/Cntr(USF)=0,0
Exp/Cntr=0.3,0.1

Type RM Length L Ch R = 1 ,4985    ,114,114,114
XS GIS Cut Line= 3
2165873.35645953683601.4475111672165971.83757206683536.977916879
2166044.93695456683517.180167452
#Sta/Elev= 30
       0 1505.01      .5 1504.72     3.4 1502.37    10.9  1494.7    13.8 1491.92
    15.1  1490.8    16.7 1489.61    17.7 1488.93    19.6 1487.97    22.5 1486.87
    25.3 1486.55    42.7 1485.91    45.6 1485.62    51.3 1484.62    57.1 1484.33
    62.9 1484.57    65.5  1484.9    71.6 1487.34    74.5 1488.34    75.1 1488.51
    77.4 1488.69      99 1489.55   109.1 1489.62   138.8 1490.41   142.9 1490.71
   151.2 1491.59   163.6 1492.44   180.2 1493.19   184.4 1493.19   193.4 1493.54
#Mann= 3 ,-1,0
       0      .1       0    51.3    .045       0    62.9      .1       0
Bank Sta=51.3,62.9
XS Rating Curve= 0 ,0
Exp/Cntr(USF)=0,0
Exp/Cntr=0.3,0.1

Type RM Length L Ch R = 1 ,4871    ,262.4,262.4,262.4
XS GIS Cut Line= 4
2165944.63843449683701.5939720472165969.80289691 683681.98049398
2166004.58906556683597.9755973542166036.24403118683539.885616304
#Sta/Elev= 30
       0 1497.88     7.2 1496.73    20.2 1495.34    26.7 1494.09    32.8 1492.62
    37.1 1490.99    41.4 1486.73    43.5 1485.12    45.3 1484.09    45.8 1483.79
    46.6 1483.68    50.1  1483.5    54.4  1483.5    58.7 1483.68    61.9 1484.07
    67.4 1485.18    71.7 1485.66    76.1 1485.68    84.7 1485.45    93.4 1485.88
   104.8 1485.31   110.7 1485.22     115 1485.62   120.1 1487.43   123.7 1488.89
   128.3 1489.77   132.8 1489.98     142 1490.03   155.6 1490.68     189 1492.57
#Mann= 3 ,-1,0
       0      .1       0    45.3    .045       0    61.9      .1       0
Bank Sta=45.3,61.9
XS Rating Curve= 0 ,0
Exp/Cntr(USF)=0,0
Exp/Cntr=0.3,0.1

Type RM Length L Ch R = 1 ,4609    ,160,160,160
XS GIS Cut Line= 4
2166027.17940994683840.6425871832166032.11361826  683825.4287782
2166117.63989579683740.3136847022166160.81421857 683709.47488271
#Sta/Elev= 30
       0 1504.87     7.8 1502.28    16.3 1498.69      22 1497.27    27.4 1495.44
    33.4 1492.39    38.8 1489.96    47.3 1488.07    50.2  1487.2      56 1482.81
    58.6 1482.02    61.5 1481.61    66.9 1481.45    72.31482.137    78.7 1483.15
    89.4 1484.07   106.4 1484.43   115.2 1484.09   123.3 1484.47   128.9  1484.5
   132.2 1484.82     135 1485.36   137.9  1486.4     142 1488.23   144.7 1489.23
   149.6 1490.73   159.4  1492.3   163.7 1492.82   174.2 1494.59   189.7 1496.75
#Mann= 3 ,-1,0
       0      .1       0    58.6    .045       0    72.3      .1       0
Bank Sta=58.6,72.3
XS Rating Curve= 0 ,0
Exp/Cntr(USF)=0,0
Exp/Cntr=0.3,0.1

Type RM Length L Ch R = 1 ,4449    ,164.8,164.8,164.8
XS GIS Cut Line= 4
2166098.24559521683940.9963010682166130.91357405683928.101046262
2166222.04004134683871.3619251162166294.25346826683824.939007814
#Sta/Elev= 30
       0 1504.24     6.4 1502.51    27.9 1495.66    41.3  1492.3      46 1490.86
    49.8 1489.21    55.8 1486.12    61.4 1483.71    64.3 1482.73    69.6    1482
    74.3 1481.95    78.5 1481.56    81.7 1480.63    84.6 1480.02    88.4 1479.85
    93.2 1480.57    97.9 1482.47   107.3 1487.28     112 1489.02   113.7 1489.46
   116.7 1490.17   131.5 1490.82     145 1491.95   149.8  1492.6     163 1494.94
   183.5 1499.61   202.1 1504.26   206.4 1505.67   216.3 1509.63   228.3 1513.96
#Mann= 3 ,-1,0
       0      .1       0    81.7    .045       0    93.2      .1       0
Bank Sta=81.7,93.2
XS Rating Curve= 0 ,0
Exp/Cntr(USF)=0,0
Exp/Cntr=0.3,0.1

Type RM Length L Ch R = 1 ,4284    ,196.7,196.7,196.7
XS GIS Cut Line= 3
2166200.47581198684073.1985547852166329.95902896683996.782230008
 2166376.6578941683957.512729776
#Sta/Elev= 30
       0 1499.16    18.2  1494.3    41.5 1486.28    46.1 1485.13    58.2 1482.89
    67.11479.947    69.3 1479.23    72.8  1478.8    78.6 1478.72    83.3 1478.82
    86.6 1480.16    87.9 1480.89    92.5 1484.99    97.2 1487.71   101.8 1489.32
   110.8  1491.2   113.7 1492.15   120.4 1495.18   125.1 1494.74   129.7 1493.64
   134.2 1493.06     139 1492.91   143.6 1493.62   153.2 1496.34     163 1497.44
   165.8 1498.08   174.6 1501.39   195.1  1506.2   200.3 1507.74   211.4 1511.62
#Mann= 3 ,-1,0
       0      .1       0    67.1    .045       0    86.6      .1       0
Bank Sta=67.1,86.6
XS Rating Curve= 0 ,0
Exp/Cntr(USF)=0,0
Exp/Cntr=0.3,0.1

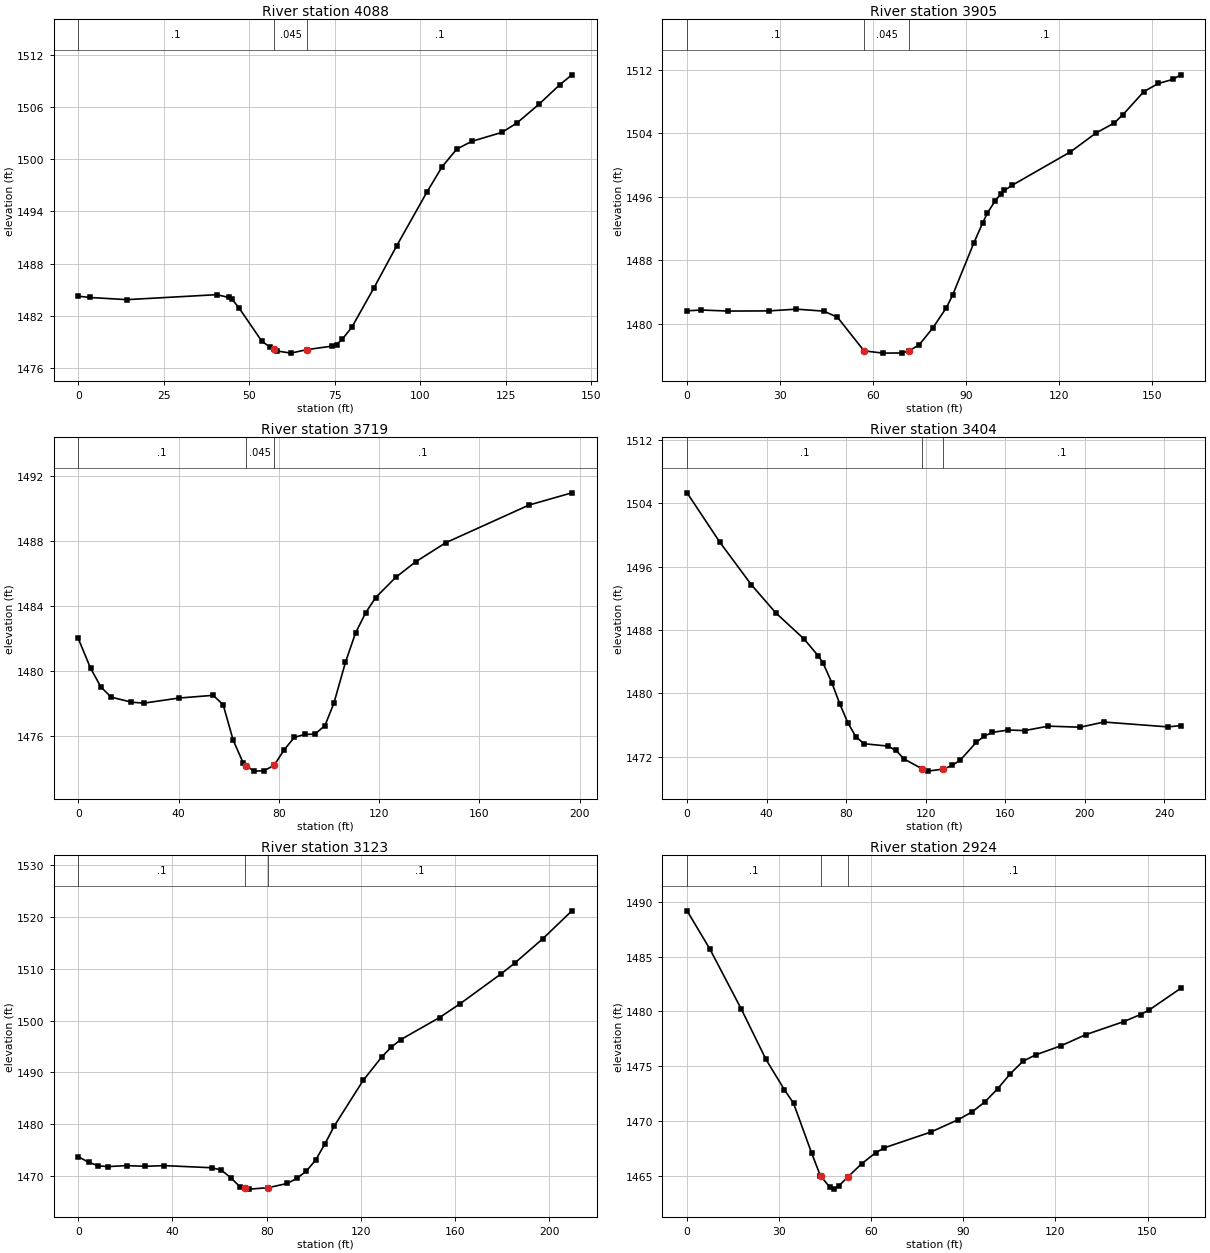
Type RM Length L Ch R = 1 ,4088    ,182.6,182.6,182.6
XS GIS Cut Line= 2
2166378.78056979684210.1111366762166438.21548906684078.505244005
#Sta/Elev= 28
       0 1484.26     3.4 1484.11    14.2 1483.86    40.5 1484.43    44.1 1484.11
    44.9 1483.96    47.1 1482.87    53.7 1479.09    56.2 1478.38    57.31478.143
    58.1 1477.97    62.2 1477.72    66.9 1478.12    74.3 1478.53    75.6 1478.71
    77.3 1479.35      80 1480.67    86.4 1485.14    93.2 1490.07     102 1496.21
   106.4 1499.09   110.7 1501.14   115.1 1502.03   123.9 1503.06   128.3 1504.13
   134.8  1506.3   140.8 1508.51   144.4 1509.67
#Mann= 3 ,-1,0
       0      .1       0    57.3    .045       0    66.9      .1       0
Bank Sta=57.3,66.9
XS Rating Curve= 0 ,0
Exp/Cntr(USF)=0,0
Exp/Cntr=0.3,0.1

Type RM Length L Ch R = 1 ,3905    ,185.5,185.5,185.5
XS GIS Cut Line= 3
 2166440.0268397684324.7008084942166547.22196195684275.879267664
2166582.24611081684253.591172938
#Sta/Elev= 30
       0 1481.66     4.6 1481.76    13.3 1481.63    26.5 1481.65    35.3 1481.87
    44.1 1481.62    48.5 1480.86    57.1 1476.62    63.2 1476.33    69.2 1476.35
    71.61476.604    74.9 1477.38    79.3  1479.5    83.7 1482.07    85.7 1483.65
    92.5 1490.18    95.4 1492.75    96.9 1493.97    99.4 1495.51   101.3 1496.42
   102.4 1496.83     105  1497.5   123.7 1501.68     132 1504.07   137.8 1505.31
   140.7 1506.39   147.4 1509.28   152.1  1510.3   156.8 1510.82   159.3 1511.39
#Mann= 3 ,-1,0
       0      .1       0    57.1    .045       0    71.6      .1       0
Bank Sta=57.1,71.6
XS Rating Curve= 0 ,0
Exp/Cntr(USF)=0,0
Exp/Cntr=0.3,0.1

Type RM Length L Ch R = 1 ,3719    ,315,315,315
XS GIS Cut Line= 3
2166407.31876587684459.5367060032166516.49858989684479.309430039
2166602.46695527684480.169113693
#Sta/Elev= 30
       0 1482.01     4.9 1480.19       9 1479.04    13.1 1478.41    21.2  1478.1
    26.2 1478.04      40 1478.35    53.8 1478.52    57.8 1477.95    61.8 1475.77
    65.9 1474.34      671474.214      70 1473.87      74 1473.89    78.1 1474.22
    82.2 1475.19    86.2 1475.94    90.3 1476.12    94.4 1476.14    98.4 1476.66
     102 1478.05   106.6 1480.55   110.6 1482.34   114.6 1483.57   118.6 1484.51
   126.6 1485.75   134.6 1486.71   146.6 1487.88   179.8 1490.19   196.9 1490.94
#Mann= 3 ,-1,0
       0      .1       0      67    .045       0    78.1      .1       0
Bank Sta=67,78.1
XS Rating Curve= 0 ,0
Exp/Cntr(USF)=0,0
Exp/Cntr=0.3,0.1

Type RM Length L Ch R = 1 ,3404    ,281.4,281.4,281.4
XS GIS Cut Line= 4
2166514.95729149684819.0613629052166552.78337226684758.883507144
2166538.16875014684657.4408360032166538.16875014684582.648358128
#Sta/Elev= 30
       0 1505.33    16.4 1499.12    32.4  1493.7    44.7 1490.15    58.9 1486.86
    66.1 1484.71    68.4 1483.84    72.8 1481.37    76.8  1478.7    80.9 1476.28
    84.9 1474.54      89 1473.64   101.1 1473.34   105.1  1472.8   109.2 1471.71
   118.41470.455   121.3 1470.18     129 1470.45   133.4  1470.9   137.5 1471.58
   145.5 1473.81   149.6 1474.61   153.6 1475.08   161.7 1475.37   169.8  1475.3
   181.8 1475.86   197.8 1475.73   209.8 1476.38   241.8 1475.77   248.4 1475.92
#Mann= 3 ,-1,0
       0      .1       0   118.4    .045       0     129      .1       0
Bank Sta=118.4,129
XS Rating Curve= 0 ,0
Exp/Cntr(USF)=0,0
Exp/Cntr=0.3,0.1

Type RM Length L Ch R = 1 ,3123    ,199.4,199.4,199.4
XS GIS Cut Line= 3
2166655.74375651684799.7898261842166805.51031896684786.817919201
2166856.21868262684756.157048148
#Sta/Elev= 30
       0 1473.73     4.4 1472.65     8.5 1471.97    12.5 1471.81    20.5    1472
    28.5 1471.87    36.6    1472    56.6 1471.59    60.7 1471.16    64.7 1469.69
    68.7 1467.91    70.81467.667    72.7 1467.46    80.7 1467.74    88.8 1468.56
    92.8 1469.54    96.8 1470.92   100.8 1473.07   104.8 1476.25   108.8 1479.71
     121 1488.47   128.9    1493   132.9 1494.86   136.9 1496.32   153.4 1500.59
   162.2 1503.28   179.7 1509.08   185.5 1511.17   197.2 1515.79   209.6  1521.2
#Mann= 3 ,-1,0
       0      .1       0    70.8    .045       0    80.7      .1       0
Bank Sta=70.8,80.7
XS Rating Curve= 0 ,0
Exp/Cntr(USF)=0,0
Exp/Cntr=0.3,0.1

Type RM Length L Ch R = 1 ,2924    ,216.5,216.5,216.5
XS GIS Cut Line= 3
 2166669.5716869685009.2559868372166752.96100131684966.271804151
2166818.29695899684951.657182037
#Sta/Elev= 30
       0 1489.17     7.4  1485.7    17.6 1480.25    25.7 1475.63    31.7 1472.87
    34.7 1471.62    40.6 1467.07    43.4 1465.04    43.6 1464.98    46.5 1463.98
    47.9 1463.81    49.5 1464.12    52.3  1464.9    56.9 1466.13    61.4 1467.12
    64.3 1467.58    79.4 1469.01    88.4 1470.15    92.9 1470.86    97.1 1471.78
   101.2 1472.97   105.3 1474.33   109.4 1475.46   113.5 1476.04   121.7 1476.86
   129.9 1477.89   142.2 1479.07   147.7 1479.72   150.4 1480.11   160.8 1482.11
#Mann= 3 ,-1,0
       0      .1       0    43.6    .045       0    52.3      .1       0
Bank Sta=43.6,52.3
XS Rating Curve= 0 ,0
Exp/Cntr(USF)=0,0
Exp/Cntr=0.3,0.1

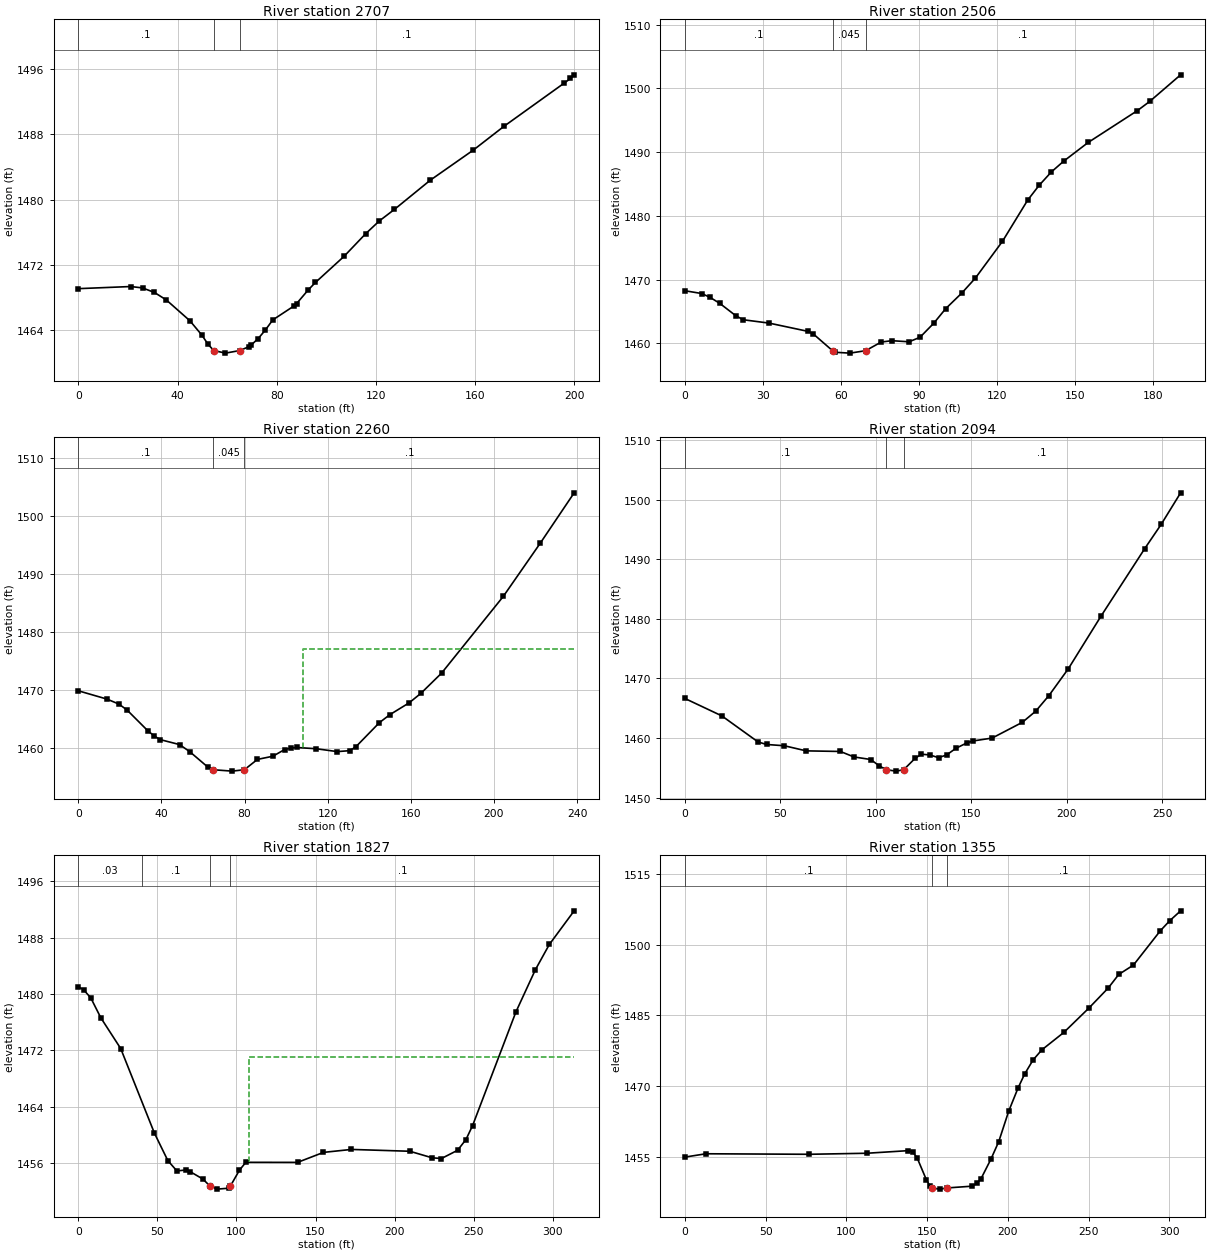
Type RM Length L Ch R = 1 ,2707    ,201.2,201.2,201.2
XS GIS Cut Line= 3
2166774.45309265685195.8073396982166905.12500802685110.698657978
2166945.53013975685093.504984903
#Sta/Elev= 30
       0 1469.08    21.1 1469.34    25.9 1469.17    30.7 1468.61    35.5 1467.69
      45 1465.14    49.8 1463.39    52.3 1462.26    54.6  1461.5    59.3 1461.18
      651461.491    68.9 1461.98    69.6 1462.15    72.5 1462.96    75.4 1464.01
    78.4 1465.25      87 1466.97      88 1467.25    92.7 1468.93    95.6 1469.84
   107.1 1473.03   115.9 1475.83   121.4 1477.39   127.4 1478.78   141.9 1482.37
   159.3 1486.07   171.6 1488.97     196 1494.29   198.4 1494.83   199.9 1495.28
#Mann= 3 ,-1,0
       0      .1       0    54.6    .045       0      65      .1       0
Bank Sta=54.6,65
XS Rating Curve= 0 ,0
Exp/Cntr(USF)=0,0
Exp/Cntr=0.3,0.1

Type RM Length L Ch R = 1 ,2506    ,246,246,246
XS GIS Cut Line= 4
2166899.39695268685366.0634665732166918.19823419685344.476810028
 2166985.0472351685284.5912467082167046.32548594685246.292339935
#Sta/Elev= 30
       0 1468.26     6.5 1467.82     9.7 1467.22    13.4 1466.29    19.5 1464.37
    22.4 1463.71    32.4 1463.18    47.4 1461.88    49.4 1461.48    56.81458.849
    57.9  1458.6    63.5 1458.47    69.5 1458.85    75.5 1460.21    79.6 1460.42
    86.2 1460.25    90.4 1460.95    95.7 1463.16   100.3 1465.45   106.5  1467.9
   111.7 1470.24   122.1    1476   131.8 1482.47   136.2 1484.79   140.9 1486.89
   145.6 1488.57   155.1 1491.53     174 1496.52   178.7 1497.95   190.6 1502.13
#Mann= 3 ,-1,0
       0      .1       0    56.8    .045       0    69.5      .1       0
Bank Sta=56.8,69.5
XS Rating Curve= 0 ,0
Exp/Cntr(USF)=0,0
Exp/Cntr=0.3,0.1

Type RM Length L Ch R = 1 ,2260    ,165.5,165.5,165.5
XS GIS Cut Line= 3
2167039.36204834 685575.662938192167135.45748716685451.713748994
2167183.50520657685385.561091839
#Sta/Elev= 30
       0 1469.91    13.8 1468.48    19.5 1467.63    23.4 1466.62    33.5 1463.01
    36.6 1462.12    39.4 1461.51    48.7 1460.66    53.6 1459.44    62.2 1456.82
    64.61456.337      74 1456.09    79.91456.329    86.2 1458.11    93.6 1458.65
    99.3 1459.81   102.1 1460.04     105 1460.16   114.5 1459.94   124.6 1459.45
   130.6 1459.61   133.5 1460.26   144.9 1464.44   149.9  1465.8   159.2 1467.84
   164.9 1469.49   174.8 1472.95   204.5 1486.15   222.2 1495.26   238.6 1503.97
#Mann= 3 ,-1,0
       0      .1       0    64.6    .045       0    79.9      .1       0
#XS Ineff= 2 , 0
                          108.29         1477.18
Permanent Ineff=
       F       F
Bank Sta=64.6,79.9
XS Rating Curve= 0 ,0
Exp/Cntr(USF)=0,0
Exp/Cntr=0.3,0.1

Type RM Length L Ch R = 1 ,2094    ,267.1,267.1,267.1
XS GIS Cut Line= 4
2167146.51942247685661.9017454882167211.51150669685626.310842224
2167258.70813928685524.954139448 2167304.3573413685466.925492821
#Sta/Elev= 30
       0 1466.64    19.4 1463.71    38.4 1459.33    42.9 1458.91    52.1  1458.7
    63.6 1457.84    81.5 1457.74    88.6 1456.82    97.4 1456.39   101.8 1455.33
   105.51454.678   110.6 1454.44   114.6 1454.66   120.6 1456.58   123.9 1457.28
   128.3 1457.16   132.9  1456.7   137.1 1457.15     142 1458.27   147.7 1459.17
   150.7 1459.49     161 1459.99   176.8 1462.63   183.8  1464.5   190.7 1467.11
   200.9 1471.63   218.1  1480.5   240.9 1491.78   249.5 1495.84   259.7 1501.14
#Mann= 3 ,-1,0
       0      .1       0   105.5    .045       0   114.6      .1       0
Bank Sta=105.5,114.6
XS Rating Curve= 0 ,0
Exp/Cntr(USF)=0,0
Exp/Cntr=0.3,0.1

Type RM Length L Ch R = 1 ,1827    ,472.8,472.8,472.8
XS GIS Cut Line= 3
2167233.94925006685818.9659490262167347.68539745685695.945218176
2167442.85237791685585.303931941
#Sta/Elev= 30
       0 1481.03     3.3 1480.63     7.9 1479.45    14.2 1476.64    26.8 1472.26
    48.1 1460.25    56.6 1456.34    62.3 1454.88    67.8    1455    70.8 1454.76
    78.7 1453.73      83 1452.78    87.8 1452.29      95 1452.42    96.2 1452.75
   101.9 1454.99   105.9  1456.1   138.6 1456.09     155 1457.51   172.7 1457.93
   209.6 1457.67   223.7 1456.74   229.6 1456.64   239.8 1457.81   245.1 1459.34
   249.3 1461.33   276.7 1477.48     289 1483.47   297.8 1487.05   313.5 1491.83
#Mann= 4 ,-1,0
       0     .03       0      40      .1       0      83    .045       0
    96.2      .1       0
#XS Ineff= 2 , 0
                          108.06         1471.04
Permanent Ineff=
       F       F
Bank Sta=83,96.2
XS Rating Curve= 0 ,0
Exp/Cntr(USF)=0,0
Exp/Cntr=0.3,0.1

Type RM Length L Ch R = 1 ,1355    ,159.6,159.6,159.6
XS GIS Cut Line= 4
2167402.72376007685906.0260654692167434.75557301685862.156408619
2167575.41701244685702.6936876882167608.14516913685679.714343623
#Sta/Elev= 30
       0 1454.91    13.1 1455.62      77 1455.51   112.7 1455.73   138.2 1456.28
     141 1456.07   143.9 1454.68   149.5 1450.12   151.6 1448.87   153.2 1448.31
     158 1448.11   162.3 1448.36   177.9 1448.74   180.7 1449.34   183.4 1450.36
   189.5 1454.49   194.3 1458.18   200.5 1464.68   206.2 1469.53   210.3 1472.53
   215.6 1475.56     221 1477.69   234.6 1481.39     250 1486.52   262.1 1490.83
   268.6 1493.71   277.7  1495.7   294.4 1503.01   300.2 1505.13   306.9 1507.22
#Mann= 3 ,-1,0
       0      .1       0   153.2    .045       0   162.3      .1       0
Bank Sta=153.2,162.3
XS Rating Curve= 0 ,0
Exp/Cntr(USF)=0,0
Exp/Cntr=0.3,0.1

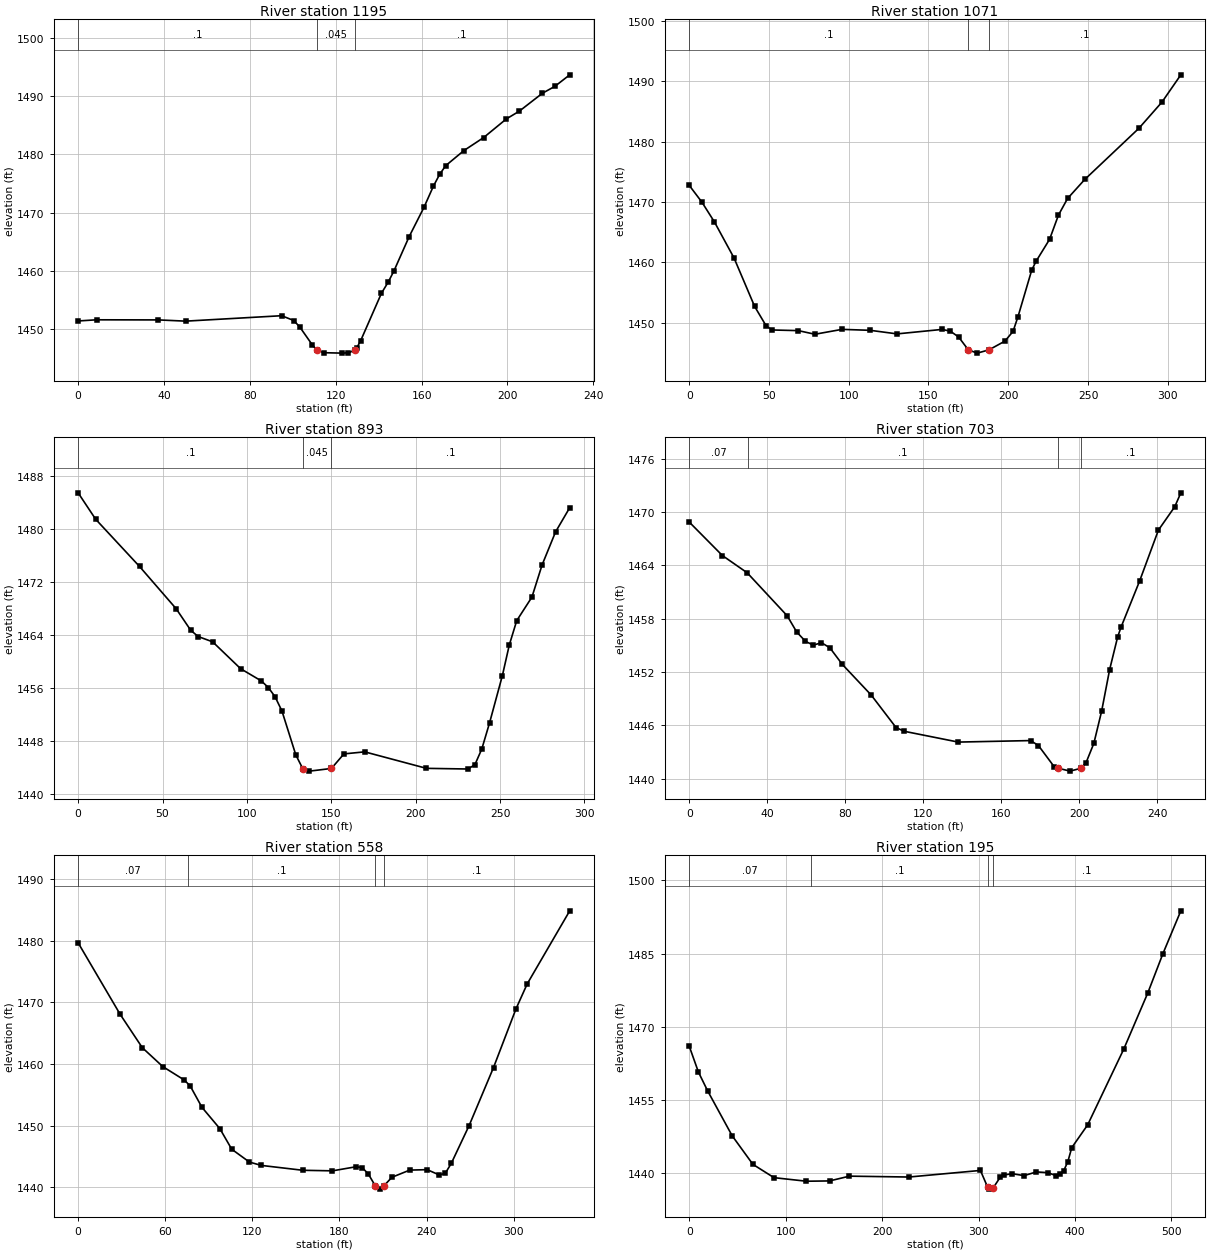
Type RM Length L Ch R = 1 ,1195    ,123.7,123.7,123.7
XS GIS Cut Line= 2
2167528.06563679685979.142160219 2167693.0991078685820.375783047
#Sta/Elev= 30
       0 1451.44     8.6 1451.64    37.4 1451.62    50.1 1451.41    94.8 1452.34
   100.5 1451.51   103.3 1450.38     109 1447.39   111.2 1446.45   114.6    1446
   123.1 1445.93   125.9 1445.99   128.8 1446.41   129.8 1446.83   131.6 1448.05
   141.3 1456.19   144.5 1458.14   147.1    1460   154.2 1465.89   161.1  1470.9
   165.5 1474.54   168.4 1476.55   171.2 1478.04   179.7 1480.63   188.9 1482.86
   199.5 1486.06   205.5 1487.38   216.3 1490.46   222.1 1491.64     229 1493.61
#Mann= 3 ,-1,0
       0      .1       0   111.2    .045       0   128.8      .1       0
Bank Sta=111.2,128.8
XS Rating Curve= 0 ,0
Exp/Cntr(USF)=0,0
Exp/Cntr=0.3,0.1

Type RM Length L Ch R = 1 ,1071    ,178.3,178.3,178.3
XS GIS Cut Line= 4
2167602.43771874686133.0483530012167609.40115634686074.555477201
2167741.70647065 685943.642850412167777.22000238685891.417068446
#Sta/Elev= 30
       0 1472.75     7.9 1469.99    15.8 1466.69    28.1 1460.71      41 1452.68
    48.2 1449.47    51.8 1448.78    68.4 1448.67    78.8 1448.07    95.8 1448.88
   113.5 1448.72   130.3 1448.13   158.5 1448.87   163.7 1448.58   168.9 1447.61
     175 1445.47   180.6 1444.94     1881445.493   197.9 1446.93     203 1448.54
   206.1 1450.97   214.7 1458.69   217.4 1460.15   225.9  1463.8   231.5 1467.84
   237.2 1470.58     248 1473.74   281.9 1482.21   296.4 1486.57   308.2 1491.08
#Mann= 3 ,-1,0
       0      .1       0     175    .045       0     188      .1       0
Bank Sta=175,188
XS Rating Curve= 0 ,0
Exp/Cntr(USF)=0,0
Exp/Cntr=0.3,0.1

Type RM Length L Ch R = 1 ,893     ,190.3,190.3,190.3
XS GIS Cut Line= 4
2167771.66296453686234.7993807842167804.15900664686156.654136659
2167838.20247933685987.9842037972167855.22421567685957.809307551
#Sta/Elev= 30
       0 1485.44    10.4 1481.45    36.4 1474.32    58.1 1467.94    66.7  1464.7
    71.1 1463.75    79.7 1462.95    96.3 1458.89   108.6 1457.04   112.7 1456.05
   116.7 1454.66   120.8 1452.49     129 1445.87   133.1 1443.81   137.1 1443.43
   150.11443.833   157.5 1446.03   169.8 1446.34   206.4 1443.85     231 1443.75
   235.1  1444.4   239.2 1446.77   243.8 1450.72   251.4 1457.86   255.5 1462.48
   259.9 1466.15   268.9  1469.7   274.9 1474.54   282.9 1479.54   291.3  1483.2
#Mann= 3 ,-1,0
       0      .1       0   133.1    .045       0   150.1      .1       0
Bank Sta=133.1,150.1
XS Rating Curve= 0 ,0
Exp/Cntr(USF)=0,0
Exp/Cntr=0.3,0.1

Type RM Length L Ch R = 1 ,703     ,144.1,144.1,144.1
XS GIS Cut Line= 4
2167940.33289739686257.2371241462167975.92380066686155.106706082
2167993.71925229686046.0128504242168003.77755104686014.290523601
#Sta/Elev= 30
       0 1468.89      17 1465.12    29.7 1463.18    50.2 1458.34    55.1 1456.51
    59.6 1455.46    63.6 1455.03    67.8 1455.31    72.1 1454.73    78.5 1452.86
    93.3 1449.41     106 1445.76   110.1 1445.34   137.9 1444.12     175 1444.29
     179 1443.73   187.1 1441.34     1891441.186   195.2 1440.85   200.6 1441.16
   203.3 1441.74   207.4 1443.97   211.4  1447.6   215.5 1452.28   219.6 1455.95
   221.3 1457.03   230.9 1462.27   240.5 1467.98   248.9 1470.62     252 1472.18
#Mann= 4 ,-1,0
       0     .07       0      30      .1       0     189    .045       0
   200.6      .1       0
Bank Sta=189,200.6
XS Rating Curve= 0 ,0
Exp/Cntr(USF)=0,0
Exp/Cntr=0.3,0.1

Type RM Length L Ch R = 1 ,558     ,363.5,363.5,363.5
XS GIS Cut Line= 4
2168059.35383873  686351.8172711 2168076.4529466686288.449988984
2168119.23940205686084.7307535592168127.67289869686020.512384625
#Sta/Elev= 30
       0 1479.67    28.9 1468.07    44.2 1462.64    58.3 1459.57    73.1 1457.39
    77.2 1456.42    85.3 1452.95    97.6  1449.5   105.8 1446.15     118 1444.06
   126.2 1443.52   154.8 1442.73   175.2 1442.64   191.6 1443.31   195.7 1443.15
   199.8 1442.16   204.7 1440.19   207.9 1439.67   210.61440.199   216.1 1441.59
   228.4 1442.76   240.4 1442.83   248.8 1441.97   252.9 1442.25     257 1443.84
   269.3 1449.99   286.1 1459.41   301.6 1468.95   309.3 1472.99   338.6 1484.86
#Mann= 4 ,-1,0
       0     .07       0   75.63      .1       0   204.7    .045       0
   210.6      .1       0
Bank Sta=204.7,210.6
XS Rating Curve= 0 ,0
Exp/Cntr(USF)=0,0
Exp/Cntr=0.3,0.1

Type RM Length L Ch R = 1 ,195     ,,,
XS GIS Cut Line= 4
 2168254.3300914686475.689088767 2168302.3778108686430.426744398
2168383.15368691686097.5744273452168355.99628029686000.086301012
#Sta/Elev= 30
       0 1466.04     9.5 1460.75      19 1456.91    44.5 1447.68      66 1441.82
    87.9 1439.09   121.5 1438.36   145.5 1438.42   166.1  1439.4   227.8 1439.22
   301.9 1440.57   309.51437.083   311.1 1436.74   315.3 1437.04   322.5  1439.2
   326.6 1439.65   334.8  1439.9   347.2 1439.51     360 1440.27   371.9 1440.11
   380.1 1439.52   384.2 1439.75   388.3 1440.54   392.5 1442.34   396.6 1445.24
   413.1 1449.91   450.5 1465.43   475.4 1476.93   491.1 1484.99   509.7 1493.78
#Mann= 4 ,-1,0
       0     .07       0  126.01      .1       0   309.5    .045       0
   315.3      .1       0
Bank Sta=309.5,315.3
XS Rating Curve= 0 ,0
Exp/Cntr(USF)=0,0
Exp/Cntr=0.3,0.1
LCMann Table=0

Chan Stop Cuts=-1
Use User Specified Reach Order=0
Composite Channel Slope=5